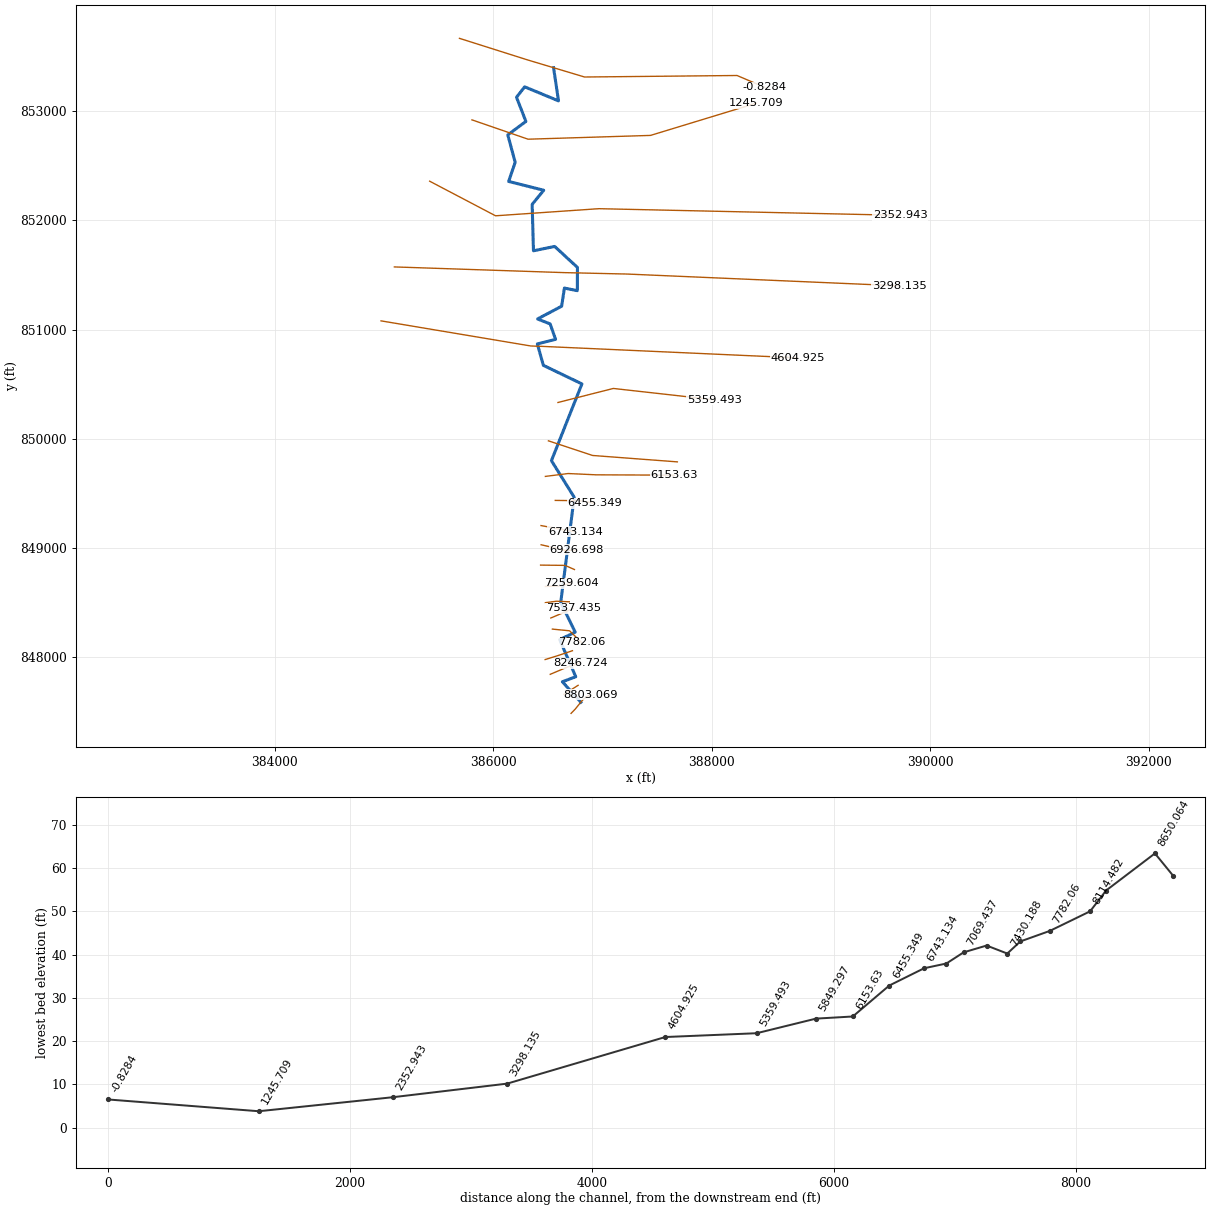
--- 6944_ras.prj (project) ---

Proj Title=6944
Current Plan=p01
Default Exp/Contr=0.3,0.1
English Units
Geom File=g01
Flow File=f01
Plan File=p01
Y Axis Title=Elevation
X Axis Title(PF)=Main Channel Distance
X Axis Title(XS)=Station
BEGIN DESCRIPTION:
RFD model 6944 exported to HEC-RAS
END DESCRIPTION:

--- 6944_ras.p01 (plan) ---

Plan Title=Plan 01
Program Version=4.10
Short Identifier=Plan 01
Geom File=g01
Flow File=f01
Subcritical Flow
Calc Critical at every XS
Secant Critical Depth

--- 6944_ras.f01 (steady flow) ---

Flow Title=Flow 01
Program Version=5.01
Number of Profiles= 6
Profile Names=10yr,25yr,50yr,100yr,100plus,500yr
River Rch & RM=6944,20,8803.069
  192.97  320.35  443.04  560.14  817.81 1448.42
River Rch & RM=6944,20,8650.064
  194.31  322.58  446.13  564.06  823.53 1457.15
River Rch & RM=6944,20,8246.724
  201.94  335.46  464.15  587.05  857.09  1509.1
River Rch & RM=6944,20,8114.482
  203.48  338.08  467.83  591.76  863.98 1519.83
River Rch & RM=6944,20, 7782.06
  205.97   342.3  473.76  599.33  875.03 1536.95
River Rch & RM=6944,20,7537.435
  212.67   353.7   489.8   619.9  905.06 1583.63
River Rch & RM=6944,20,7259.604
  219.31  365.02  505.72  640.32  934.87 1629.78
River Rch & RM=6944,20,7069.437
  222.03  369.64  512.23  648.66  947.04 1648.51
River Rch & RM=6944,20,6926.698
  222.63  370.66  513.66   650.5  949.73 1652.66
River Rch & RM=6944,20,6743.134
  231.58  385.91  535.13  678.03  989.92 1714.44
River Rch & RM=6944,20,6455.349
  235.18  392.03  543.73  689.03 1005.99 1738.91
River Rch & RM=6944,20, 6153.63
  239.84  399.99  554.97  703.49  1027.1 1771.33
River Rch & RM=6944,20,5849.297
  243.56  406.38  564.01  715.14  1044.1  1797.5
River Rch & RM=6944,20,5359.493
   248.5  414.82  575.91  730.42 1066.42 1831.49
Boundary for River Rch & Prof#=6944,20,1
Up Type= 0
Dn Type= 2
Boundary for River Rch & Prof#=6944,20,2
Up Type= 0
Dn Type= 2
Boundary for River Rch & Prof#=6944,20,2
Up Type= 0
Dn Type= 2
Boundary for River Rch & Prof#=6944,20,2
Up Type= 0
Dn Type= 2
Boundary for River Rch & Prof#=6944,20,2
Up Type= 0
Dn Type= 2
Boundary for River Rch & Prof#=6944,20,2
Up Type= 0
Dn Type= 2

--- 6944_ras.g01 (geometry) ---

Geom Title=6944
Program Version=4.10

River Reach=6944,20
Reach XY= 30
386801.435195044847587.417091206386632.164361715847775.437924549
386754.560195029847821.271257877386607.685195029848160.854591236
386749.351861805848229.604591221386617.060195029848502.000424549
386740.324083939849465.194868997386531.817139506849800.090702355
386811.074228615850502.719463915386457.775617495850672.858352765
 386403.08811748850869.038908362386569.754784182850910.705575019
386520.275617495851052.198630571386404.390200838851097.337519452
386625.310339719851214.090991691386650.661178827851380.309162989
386768.716734394851356.698051885 386770.10562329851569.198051855
386561.772289976851761.559162974386367.327845514851721.975829661
386355.392081723852146.715412974386461.294859394852276.055690765
386140.114303827852356.784857422386200.010137349852532.132079631
386132.301803827852783.000135198386298.100414962852906.264024079
386212.162914976 853127.61819078386286.815692738 853223.10430187
386596.711526141853094.632079646386551.317673355853398.390605181

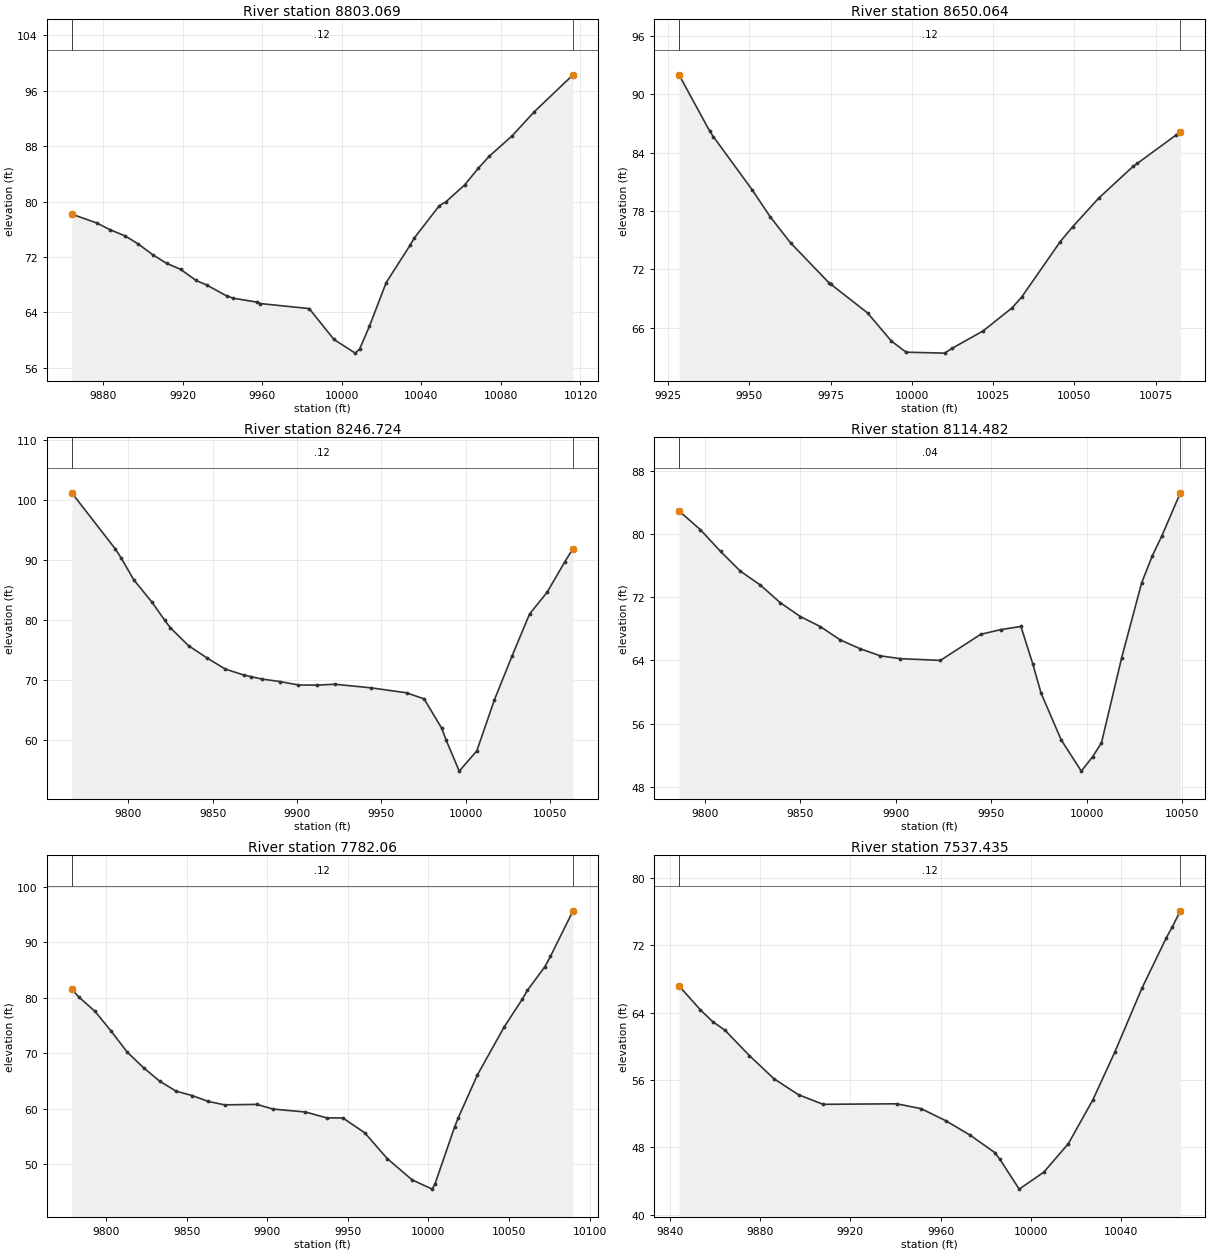
Type RM Length L Ch R = 1 ,8803.069,153.005800,153.005800,153.005800
XS GIS Cut Line= 6
386711.680321369847485.842673343386749.177384471847524.195540927
386809.505025415847598.795001528386823.437547703 847613.86393561
386853.483303525847637.384710589386892.204540917847657.617947833
#Sta/Elev= 30
9864.25478.18942 9877.0676.887169883.30775.961119891.04675.053739897.61173.89639
9905.03172.326399911.91671.087799918.95470.226099926.79568.609689932.17267.95109
9942.08766.39099 9945.3966.058699957.37965.48561 9959.13  65.2769983.61264.55675
9996.09960.0941710006.7758.1247310008.98 58.718110013.8861.9771510022.3368.30458
10034.4173.7226710036.39 74.718210049.0979.4241710052.4779.9896110061.7982.41576
 10068.784.8298510074.2786.5828710085.5689.4656510096.84 92.986210116.2598.29794
#Mann= 3 , 0 , 0
9864.254    0.12       09864.254    0.12       010116.25    0.12       0
#XS Ineff= 2 , 0
       0                               0
Bank Sta=9864.254,10116.25
Exp/Cntr=0.3,0.1

Type RM Length L Ch R = 1 ,8650.064,403.339700,403.339700,403.339700
XS GIS Cut Line= 2
386646.080308368847659.933732571386776.171969804847742.768853092
#Sta/Elev= 23
9928.40691.994139937.83886.19232 9938.9885.624069950.83580.196369956.45777.39178
 9962.6974.718599974.54570.596889975.07570.465239986.40167.507339993.69364.62519
9998.25663.4693710010.1163.3735510012.3163.8510710021.9765.6604210030.9368.05043
10033.8269.1451110045.6874.8385910049.5576.3888810057.5379.3178510068.1782.60097
10069.39 82.884710081.2485.7850510082.6386.09949
#Mann= 3 , 0 , 0
9928.406    0.12       09928.406    0.12       010082.63    0.12       0
#XS Ineff= 2 , 0
       0                               0
Bank Sta=9928.406,10082.63
Exp/Cntr=0.3,0.1

Type RM Length L Ch R = 1 ,8246.724,132.241700,132.241700,132.241700
XS GIS Cut Line= 3
386521.080308363847843.527482599386681.236558378847911.235815927
386799.726141706847946.392065942
#Sta/Elev= 30
9766.318101.25149792.288 91.8522 9795.7890.314799803.14586.728249814.00182.97948
9821.46179.995369824.858 78.72689835.71575.716879846.57273.697389857.42971.83505
9868.28670.854939872.82370.561489879.143  70.173    9890 69.74419900.85769.17766
9911.71469.150299922.57169.301469944.12468.694899964.98667.871449975.41766.85933
9985.84861.971929988.58859.923979996.279 54.798810006.7158.1869210017.1466.68736
10027.57 73.9885   1003881.0226910048.4384.6551410058.8689.7007410063.7991.95313
#Mann= 3 , 0 , 0
9766.318    0.12       09766.318    0.12       010063.79    0.12       0
#XS Ineff= 2 , 0
       0                               0
Bank Sta=9766.318,10063.79
Exp/Cntr=0.3,0.1

Type RM Length L Ch R = 1 ,8114.482,332.421900,332.421900,332.421900
XS GIS Cut Line= 3
386474.298451329847978.539147005386592.694891699848015.402482569
386724.205308385848059.673315953
#Sta/Elev= 27
9786.38882.894649797.59780.515659808.122 77.78019818.54475.272749829.01773.52156
9839.491 71.27849849.964 69.53959860.43868.266229870.91166.578169881.38565.46184
9891.85864.570479902.33264.212959923.37463.990849944.47767.287879955.02967.88782
 9965.5868.280739971.81763.532279976.13159.861689986.68353.941649997.23449.98682
10003.1651.8075910007.7953.5554910018.3464.2826910028.8973.82417 10034.577.24987
10039.4479.7311310049.1585.18698
#Mann= 3 , 0 , 0
9786.388    0.04       09786.388    0.04       010049.15    0.04       0
#XS Ineff= 2 , 0
       0                               0
Bank Sta=9786.388,10049.15
Exp/Cntr=0.3,0.1

Type RM Length L Ch R = 1 , 7782.06,244.625300,244.625300,244.625300
XS GIS Cut Line= 3
386540.611558363848257.589982599386698.163641706848241.964982584
386807.538641691848135.194149256
#Sta/Elev= 30
 9778.5981.52591    978380.127549793.04977.537149803.09873.955439813.14770.14525
9823.19667.363959833.24664.930049843.29563.155889853.34462.343789863.39361.28757
9873.44260.67161 9893.5460.751449903.589 59.90589923.68759.376629936.915 58.3219
9946.88658.307559960.44455.636859974.41950.985439989.83347.1408610002.37 45.4645
10004.1546.4577710016.3456.7382810018.46 58.285710030.3266.01341 10047.174.76144
10058.2779.7279510061.4181.3133410072.2485.5671110075.7387.4403810089.7695.67595
#Mann= 3 , 0 , 0
 9778.59    0.12       0 9778.59    0.12       010089.76    0.12       0
#XS Ineff= 2 , 0
       0                               0
Bank Sta=9778.59,10089.76
Exp/Cntr=0.3,0.1

Type RM Length L Ch R = 1 ,7537.435,107.247600,107.247600,107.247600
XS GIS Cut Line= 2
386526.288641691848359.152482599386730.715725034848446.392065927
#Sta/Elev= 23
9844.06667.156159853.53764.305459858.96462.91924 9864.4161.895659875.28258.87339
9886.15556.126979897.02754.23155  9907.953.093339940.517 53.1555 9951.3952.57845
9962.26251.153869973.13549.428329984.00747.368799986.351 46.5485 9994.88 43.0188
10005.7545.0267310016.6348.40427 10027.553.6041310037.3159.3207110049.2466.85357
10060.1272.8822510062.7874.1828810066.3376.07857
#Mann= 3 , 0 , 0
9844.066    0.12       09844.066    0.12       010066.33    0.12       0
#XS Ineff= 2 , 0
       0                               0
Bank Sta=9844.066,10066.33
Exp/Cntr=0.3,0.1

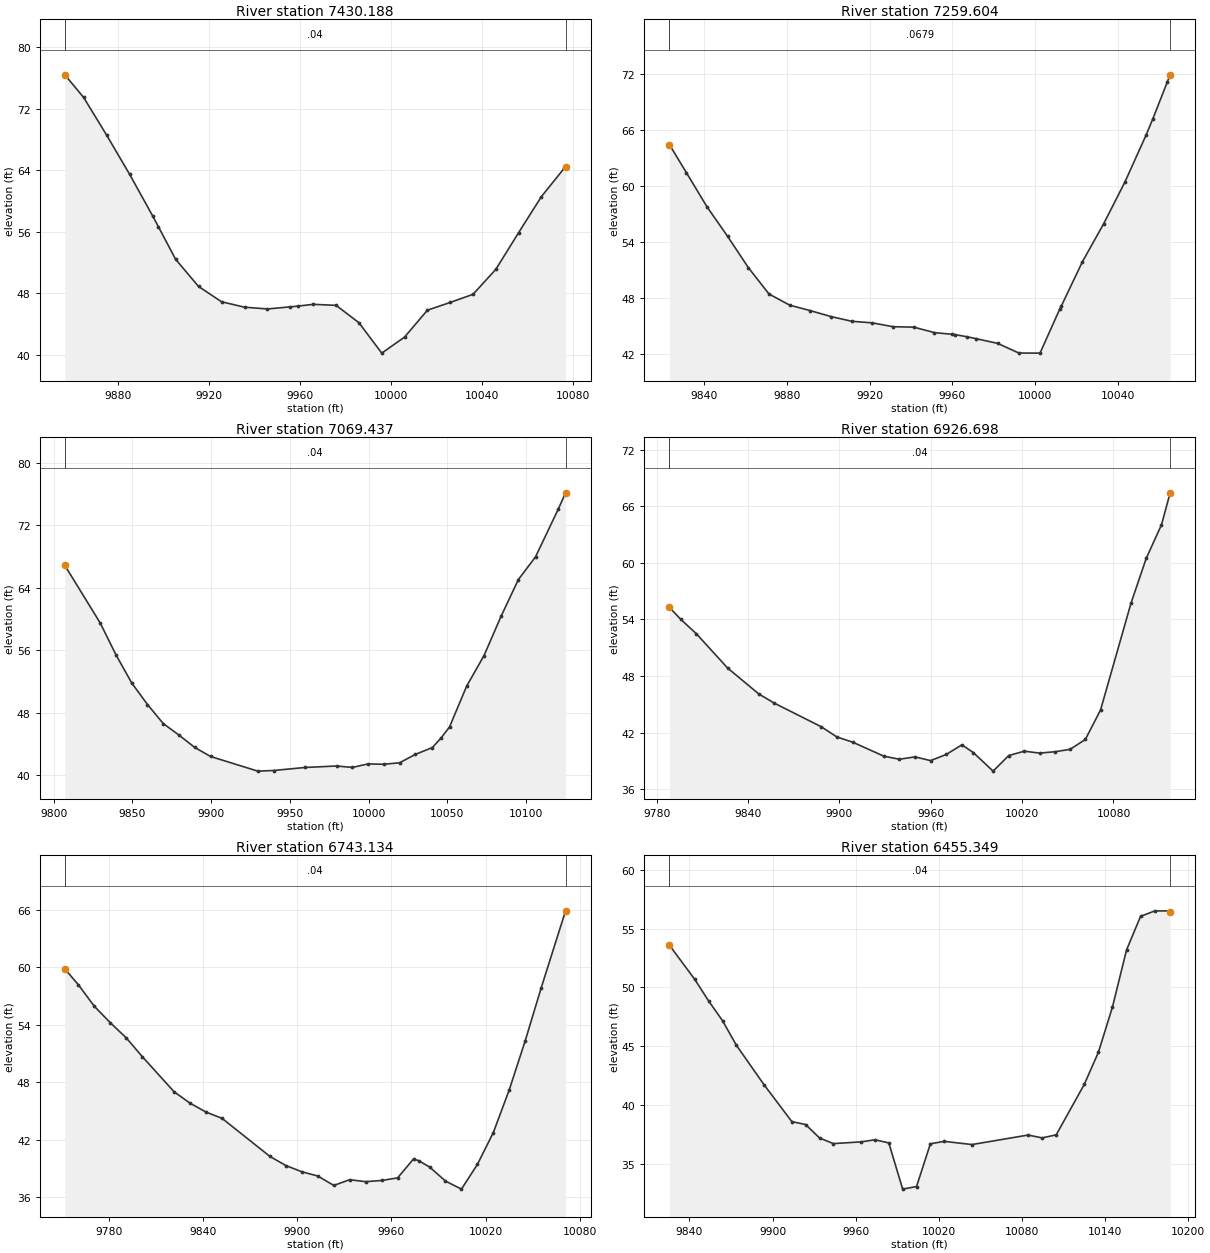
Type RM Length L Ch R = 1 ,7430.188,170.583500,170.583500,170.583500
XS GIS Cut Line= 3
386476.809475049848499.777482584386578.371975034848512.798315927
386695.559475049848507.589982599
#Sta/Elev= 26
9856.85576.434439865.11373.489869875.19568.591269885.27763.491759895.35958.09733
9897.92456.66772 9905.4452.443629915.52248.900999925.60446.909489935.68646.20318
9945.768 45.9726 9955.8546.248239959.24946.347919965.88446.574129975.89446.44235
9985.90344.176899995.91340.2260610005.9242.3138210015.9345.8117510025.9446.82145
10035.9547.8765710045.9651.1287110055.9755.9094110065.9860.6014110075.9964.28744
10076.55 64.4069
#Mann= 3 , 0 , 0
9856.855    0.04       09856.855    0.04       010076.55    0.04       0
#XS Ineff= 2 , 0
       0                               0
Bank Sta=9856.855,10076.55
Exp/Cntr=0.3,0.1

Type RM Length L Ch R = 1 ,7259.604,190.166700,190.166700,190.166700
XS GIS Cut Line= 3
386476.809475049848648.214982584386613.528225049848653.423315927
386716.392808363848676.860815927
#Sta/Elev= 30
 9823.0364.428449831.22661.434819841.233 57.75679851.24154.581019861.248 51.2384
9871.25548.408819881.26247.21745 9891.2746.628279901.27745.992499911.28445.49159
9921.291 45.31659931.299 44.90689941.30644.860839951.313 44.27259959.84744.09615
9961.35744.060649966.94543.832729971.61343.61868 9981.8743.123229992.12642.08607
10002.3842.0755410011.9646.8093610012.6447.0977710022.8951.8685710033.15 55.9287
10043.4160.3885410053.6665.4237510056.9767.1871510063.9271.1053510065.3571.91015
#Mann= 3 , 0 , 0
 9823.03  0.0679       0 9823.03  0.0679       010065.35  0.0679       0
#XS Ineff= 2 , 0
       0                               0
Bank Sta=9823.03,10065.35
Exp/Cntr=0.3,0.1

Type RM Length L Ch R = 1 ,7069.437,142.739400,142.739400,142.739400
XS GIS Cut Line= 3
386432.538641691848843.527482584386656.496975049848840.923315927
386742.434475034848803.162899271
#Sta/Elev= 28
 9807.1566.859959829.61359.483859839.61355.405969849.61451.799919859.61549.03989
9869.61546.601239879.61645.120699889.61743.538289899.61842.38476 9929.6240.50416
 9939.6240.582789959.62240.972989979.62341.161429989.62440.977799999.62441.42815
10009.6241.3824310019.6341.5724810029.6342.6451610040.41 43.525610045.8544.72534
10051.3346.1623610062.2651.4145810073.1855.28732 10084.1  60.35910095.0265.04268
10105.9567.9636810120.4274.0957210124.9976.15876
#Mann= 3 , 0 , 0
 9807.15    0.04       0 9807.15    0.04       010124.99    0.04       0
#XS Ineff= 2 , 0
       0                               0
Bank Sta=9807.15,10124.99
Exp/Cntr=0.3,0.1

Type RM Length L Ch R = 1 ,6926.698,183.563900,183.563900,183.563900
XS GIS Cut Line= 3
386437.746975049849029.725399271386664.309475049848977.642065927
386760.663641706848982.850399256
#Sta/Elev= 28
9788.26655.286979795.708 54.01759805.96952.489889826.49148.855119847.01246.10116
9857.27345.121279888.05642.626049898.31641.541529908.57740.998299929.09939.50981
 9939.3639.180939949.62139.430359959.88139.034759970.142 39.68779980.40340.70663
9987.89639.8949410000.9237.9204310011.1939.5745510021.4340.0340710031.4439.83318
10041.4639.9756210051.4740.2276210061.49 41.2748 10071.544.3955810091.5355.73086
10101.5560.4944710111.5664.0419810117.23   67.43
#Mann= 3 , 0 , 0
9788.266    0.04       09788.266    0.04       010117.23    0.04       0
#XS Ineff= 2 , 0
       0                               0
Bank Sta=9788.266,10117.23
Exp/Cntr=0.3,0.1

Type RM Length L Ch R = 1 ,6743.134,287.785200,287.785200,287.785200
XS GIS Cut Line= 2
386436.444891706849205.506649271386750.246975049849148.214982599
#Sta/Elev= 30
 9751.9259.820269760.61658.158689770.78155.911059780.94754.198849791.11252.61454
9801.27750.665099821.60846.982659831.77345.796739841.93844.871699852.10444.21858
  9882.640.240789892.76539.28919 9902.9338.641429913.095 38.19749923.26137.21437
9933.42637.811759943.59137.608559953.75737.732329963.92238.003269974.08739.98704
9977.45339.788419984.25339.143579994.41837.6710710004.5836.8284710014.7539.41095
10024.9142.7388710035.08 47.219310045.24 52.340910055.4157.8576610070.9165.89337
#Mann= 3 , 0 , 0
 9751.92    0.04       0 9751.92    0.04       010070.91    0.04       0
#XS Ineff= 2 , 0
       0                               0
Bank Sta=9751.92,10070.91
Exp/Cntr=0.3,0.1

Type RM Length L Ch R = 1 ,6455.349,301.719100,301.719100,301.719100
XS GIS Cut Line= 3
386566.653225034849435.975399256386789.309475049849433.371232584
386926.028225049849409.933732584
#Sta/Elev= 29
9825.52453.602199843.87250.680179853.87348.847299863.87347.174549873.87445.08241
9893.87541.713649913.87738.585959923.87738.330449933.87837.189539943.87936.71006
 9963.88 36.85749973.88137.036329983.882 36.76799993.88232.8352310003.8833.05581
10013.8836.6935710023.8836.9014910043.8936.6296910084.4137.4386410094.5537.19657
 10104.737.4571810124.9941.7621410135.1444.4829710145.2848.3336410155.43 53.1843
10165.5756.0578910175.7256.5104310185.8756.5247310186.9156.46538
#Mann= 3 , 0 , 0
9825.524    0.04       09825.524    0.04       010186.91    0.04       0
#XS Ineff= 2 , 0
       0                10123.85       0
Bank Sta=9825.524,10186.91
Exp/Cntr=0.3,0.1

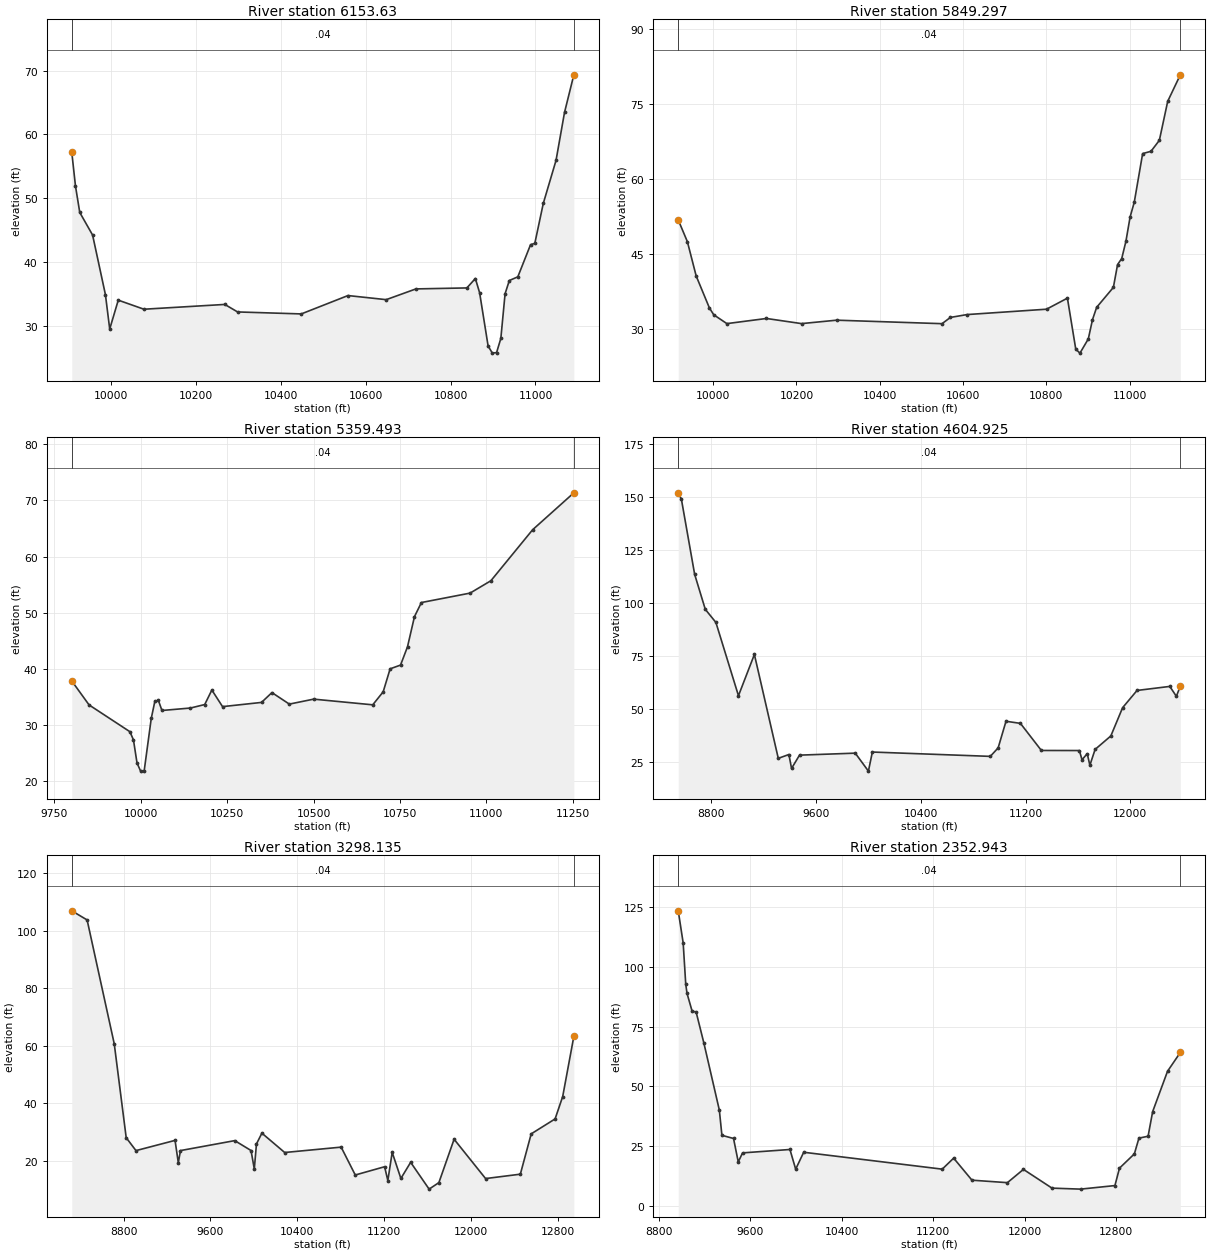
Type RM Length L Ch R = 1 , 6153.63,304.332500,304.332500,304.332500
XS GIS Cut Line= 4
386476.340617635849655.834410563386685.142808357849682.069149285
386944.092420902849670.232370445387656.947281488849667.213733335
#Sta/Elev= 30
9907.88757.191829916.61551.882839926.69347.743729956.92944.197539987.165 34.8473
9997.24429.45817 10017.433.9837110077.87 32.562510268.3433.3130910298.3832.13619
10448.4631.8252810558.4634.7060610648.4634.0627910718.4635.7473310838.4635.90274
10858.4637.3788710868.4635.1543310888.4626.8029810898.4625.6763210908.4625.76662
10918.4627.9790710928.4634.9941610938.4637.0652410958.4637.6427110988.4642.68748
10998.4642.8845211018.4649.1621611048.4655.9049811068.46 63.432111090.4169.32537
#Mann= 3 , 0 , 0
9907.887    0.04       09907.887    0.04       011090.41    0.04       0
#XS Ineff= 2 , 0
       0                10217.78       0
Bank Sta=9907.887,11090.41
Exp/Cntr=0.3,0.1

Type RM Length L Ch R = 1 ,5849.297,489.804000,489.804000,489.804000
XS GIS Cut Line= 3
386504.153225034849981.548315927386909.101141691849847.433732584
387685.142808378849788.839982599
#Sta/Elev= 30
9916.41651.830939938.37647.469849959.44540.623049991.04734.2541710001.5832.85075
10033.1831.0853710128.0932.1134710212.2631.0873910296.5431.7720510549.48 31.0724
10569.54 32.322610609.6532.8953810800.1933.9671210850.3336.1804210870.3925.97054
10880.4225.1813510900.4828.02645 10910.531.8719410920.5334.3479410960.6538.33211
10970.68  42.892 10980.744.1092810990.73 47.552911000.7652.4138611010.79 55.3817
11030.8565.09949 11050.9 65.552711070.9667.7490511091.0275.5568911121.2580.85363
#Mann= 3 , 0 , 0
9916.416    0.04       09916.416    0.04       011121.25    0.04       0
#XS Ineff= 2 , 0
       0                10135.16       0
Bank Sta=9916.416,11121.25
Exp/Cntr=0.3,0.1

Type RM Length L Ch R = 1 ,5359.493,754.568600,754.568600,754.568600
XS GIS Cut Line= 3
386591.912987094850332.710526957 387098.85743154850461.182749185
388023.541994675850357.557272149
#Sta/Elev= 30
9800.08937.866389850.11533.599979968.33128.830959978.64727.379389988.96323.26596
9999.27921.82517 10009.621.8089810030.2331.2048810040.5434.2173210050.8634.39524
10061.1832.6072510143.7133.0449610184.9733.66572 10205.636.2473910236.5533.29353
10349.36 34.043310379.5535.7938210429.8733.74272 10500.334.6264910671.3733.61502
10701.5635.9306210721.6840.0235910751.8740.6941510771.9943.9503710792.1249.31302
10812.2451.8294310953.1253.50603 11013.555.7145311134.2564.7917511253.5371.36227
#Mann= 3 , 0 , 0
9800.089    0.04       09800.089    0.04       011253.53    0.04       0
#XS Ineff= 2 , 0
       0                10077.42       0
Bank Sta=9800.089,11253.53
Exp/Cntr=0.3,0.1

Type RM Length L Ch R = 1 ,4604.925,1306.789200,1306.789200,1306.789200
XS GIS Cut Line= 4
384971.253264923851080.106360276 386342.78104269850850.071638101
386464.308820434850845.731360261388785.267496165850741.388744375
#Sta/Elev= 30
 8547.09  152.048571.169149.06288672.566113.62158753.68397.16289  8834.890.98122
9007.175 56.45689128.85175.884819311.36526.952159392.48328.759589412.76222.20696
  9473.628.459549899.466 29.398510000.0320.9303210030.0529.9223810930.9527.88056
10991.0131.8795411051.0744.4237111161.1843.4310211321.35 30.661911611.6430.62898
11631.66 26.2857 11671.729.1528411691.7223.6886811731.7631.1633911851.8837.49547
11941.9750.8251712052.0858.9378912302.3360.8407312352.3956.1877312382.6860.88504
#Mann= 3 , 0 , 0
 8547.09    0.04       0 8547.09    0.04       012382.68    0.04       0
#XS Ineff= 2 , 0
       09753.994        10522.73       0
Bank Sta=8547.09,12382.68
Exp/Cntr=0.3,0.1

Type RM Length L Ch R = 1 ,3298.135,945.192900,945.192900,945.192900
XS GIS Cut Line= 4
385093.649098228851574.029971433386645.732431545851521.946638086
387225.000000013851508.791544431389717.631923807851400.967435283
#Sta/Elev= 30
8322.021106.97198463.451103.80078713.59260.692258823.65428.051688913.70523.55587
9273.90727.114629303.92419.350429323.93623.569949824.21727.031599974.27123.58577
10004.2817.1732510024.2825.87976 10074.329.6250510284.3522.8983510804.7224.76915
10934.8415.07388 11205.1 17.947311235.1213.1560511275.1622.9438711355.2413.87353
11445.3219.4823111615.4810.1573211705.5612.4260911845.69 27.510812135.9713.83172
12456.2715.3554712556.3629.3824112776.5634.5789612846.6342.3670612949.3663.29765
#Mann= 3 , 0 , 0
8322.021    0.04       08322.021    0.04       012949.36    0.04       0
#XS Ineff= 2 , 0
       0 9415.17         10082.5       0
Bank Sta=8322.021,12949.36
Exp/Cntr=0.3,0.1

Type RM Length L Ch R = 1 ,2352.943,1107.233700,1107.233700,1107.233700
XS GIS Cut Line= 4
385416.855116725 852359.04154548386020.153727829852042.201267689
386966.334283382852107.305434346389726.750950083 852046.54154548
#Sta/Elev= 30
8971.272123.42769014.357110.04289036.94892.706119048.24388.863829093.423 81.3339
9127.30981.17932 9195.0868.209169330.62340.099719353.21329.52189 9454.8728.20007
9496.13918.398499533.93622.173379948.25323.593369998.37115.3600610068.54 22.4366
11279.9615.3668711379.9819.9741611540.0210.75346 11850.19.71750911990.1315.27001
12240.197.42811312490.257.01331712790.328.50017812830.3315.7930812960.3621.75108
13000.3728.3430513080.3929.14047 13120.439.4382613250.4356.3117813362.2164.16876
#Mann= 3 , 0 , 0
8971.272    0.04       08971.272    0.04       013362.21    0.04       0
#XS Ineff= 2 , 0
       0 9861.99         10667.1       0
Bank Sta=8971.272,13362.21
Exp/Cntr=0.3,0.1

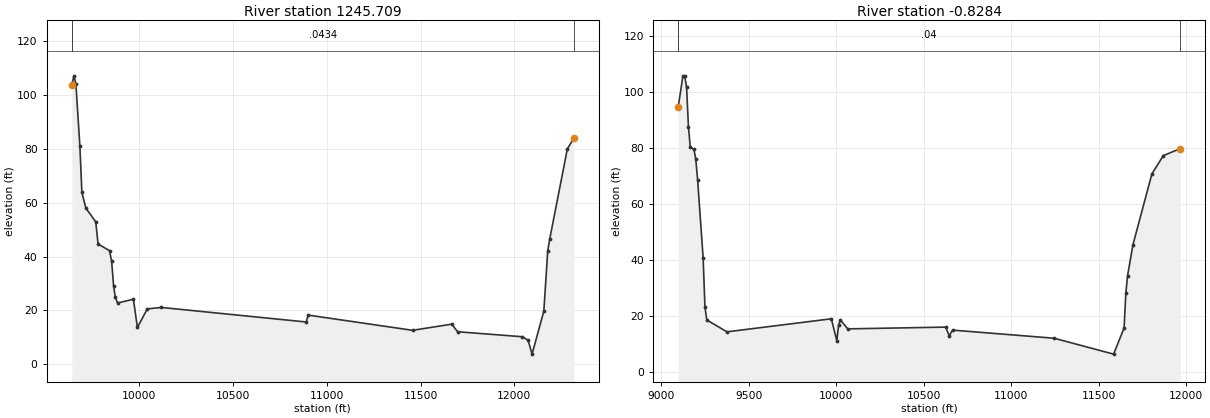
Type RM Length L Ch R = 1 ,1245.709,1246.537200,1246.537200,1246.537200
XS GIS Cut Line= 4
 385804.00789462852920.673489928386317.896783382852743.590156585
387439.424561173852778.312378809388408.174561188853073.451267704
#Sta/Elev= 30
  9639.5103.89059651.126107.21059661.704103.98839682.85880.964899693.43563.88149
9714.58958.048729767.47452.945569779.69144.71773 9841.0842.198339852.09138.30917
9862.66829.119639871.77424.929999883.82222.786579968.43924.169059989.59313.68112
10042.4820.5845710117.3321.1269210890.4915.7158610900.4918.2825411457.2912.62416
11666.3714.9170611697.7312.09419 12042.7 10.241112074.068.91351312094.973.775352
12157.6919.74953 12178.642.1688512189.0646.5132612283.1480.0458112317.8284.04562
#Mann= 3 , 0 , 0
  9639.5  0.0434       0  9639.5  0.0434       012317.82  0.0434       0
#XS Ineff= 2 , 0
       09897.827        11305.11       0
Bank Sta=9639.5,12317.82
Exp/Cntr=0.3,0.1

Type RM Length L Ch R = 1 , -0.8284,0.000000,0.000000,0.000000
XS GIS Cut Line= 5
385689.424561173853667.201267689386314.424561188853469.284601033
386835.257894516853313.034601018388231.091227919853326.923489943
388484.563450173853219.284601018
#Sta/Elev= 30
9097.09794.693219123.924105.76889134.413105.63619144.903101.67289155.39287.58713
9165.88180.39377 9186.8679.50679 9197.3576.039049207.83968.741399239.30740.95822
9249.79723.361569260.28618.68659 9375.67  14.4529972.53219.1032110003.8511.27514
10014.2917.0351110024.7318.6402310066.4915.5089510626.2116.1383310646.2113.02871
10666.2115.0661911246.2412.1670711586.266.49893711646.2615.8032611656.2628.18644
11666.2634.53886 11696.645.4337911805.24 70.781311870.4377.2973211967.7379.82169
#Mann= 3 , 0 , 0
9097.097    0.04       09097.097    0.04       011967.73    0.04       0
#XS Ineff= 2 , 0
       09786.603        11071.67       0
Bank Sta=9097.097,11967.73
Exp/Cntr=0.3,0.1